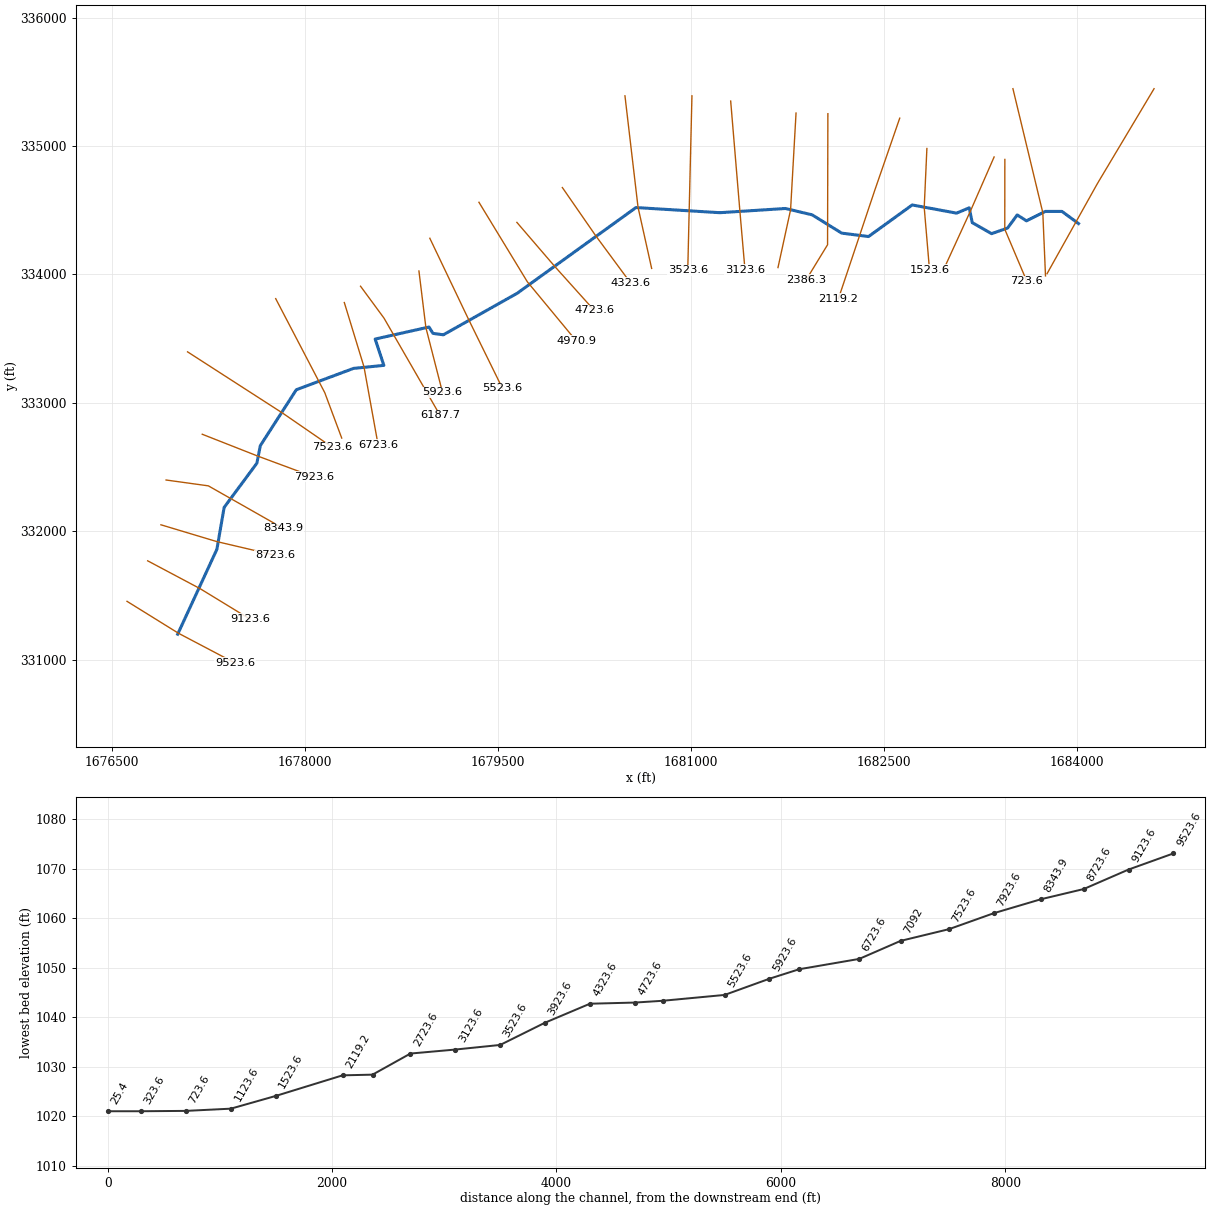
--- LTenmilCr.prj (project) ---

Proj Title=LTenmilCr
Current Plan=p01
Default Exp/Contr=0,0
English Units
Geom File=g01
Flow File=f01
Plan File=p01
BEGIN DESCRIPTION:
END DESCRIPTION:
DSS Export Rating Curves= 0
DSS Export Rating Curve Sorted= 0
DSS Export Volume Flow Curves= 0
DXF OffsetX= 0
DXF OffsetY= 0
DXF ScaleX= 0
DXF ScaleY= 0

--- LTenmilCr.p01 (plan) ---

Plan Title=Floodplain
Program Version=4.00
Geom File=g01
Flow File=f01
K Sum by GR=0
Std Step Tol=0.01
Critical Tol=0.01
Num of Std Step Trials=20
Max Error Tol=0.3
Flow Tol Ratio=0.001
Split Flow NTrial=30
Split Flow Tol=0.02
Split Flow Ratio=0.02
Log Output Level=0
Friction Slope Method=1
Unsteady Friction Slope Method=2
Unsteady Bridges Friction Slope Method=1
Global Log Level=0
CheckData=False
Run HTab=0
Run UNet=0
Run PostProcess=0
UNET Theta=0
UNET Theta Warmup=0
UNET ZTol=0
UNET ZSATol=0
UNET MxIter=0
UNET MaxInSteps=0
UNET DtIC=0
UNET DtMin=0
UNET MaxCRTS=0
UNET WFStab=0
UNET SFStab=0
UNET WFX=0
UNET SFX=0
UNET DSS MLevel=0
UNET DZMax Abort=0
UNET Convert EG Bridges=0
UNET Use Existing IB Tables=0
UNET Froude Limit=0
UNET Froude Power=0
Write IC File=0
Echo Input=False
Echo Output=False
Write Detailed=0

--- LTenmilCr.f01 (steady flow) ---

Flow Title=NFF Regression Equation
Program Version=4.00
Number of Profiles= 1
Profile Names=P100yr
River Rch & RM=LTenmilCr,Main            ,9523.6
695.9454
River Rch & RM=LTenmilCr,Main            ,9123.6
800.5936
River Rch & RM=LTenmilCr,Main            ,7923.6
874.2293
River Rch & RM=LTenmilCr,Main            ,6187.7
961.5882
River Rch & RM=LTenmilCr,Main            ,4970.9
1066.985
River Rch & RM=LTenmilCr,Main            ,3523.6
1125.022
River Rch & RM=LTenmilCr,Main            ,25.4
1214.458
Boundary for River Rch & Prof#=LTenmilCr,Main            , 1
Up Type= 0
Dn Type= 1
Dn Known WS=1021.43
DSS Import GetInterval= 0
DSS Import GetPeak= 0
DSS Import FillOption= 0

--- LTenmilCr.g01 (geometry) ---

Geom Title=USGS 3m DEM
Program Version=4.00

River Reach=LTenmilCr       ,Main
Reach XY= 30
     1677012.485      331197.755     1677317.302       331859.23
     1677373.636      332185.478     1677627.999      332529.696
     1677654.607      332666.206     1677934.543      333102.005
     1678379.332      333268.242     1678614.684      333291.745
     1678547.292      333496.685     1678965.814      333590.342
     1678996.228       333540.92     1679077.097      333529.861
     1679651.139      333853.345     1680574.022      334520.859
     1681225.822      334480.883     1681735.816        334513.6
     1681943.061      334464.067      1682172.54      334321.795
     1682381.281      334295.069     1682720.775       334541.13
      1683065.11      334477.429     1683163.949      334518.672
     1683187.219      334403.586     1683337.556      334317.531
     1683461.972      334361.306     1683536.737      334463.489
     1683608.505       334417.41     1683755.504      334490.793
     1683884.643      334490.791     1684013.216      334395.898

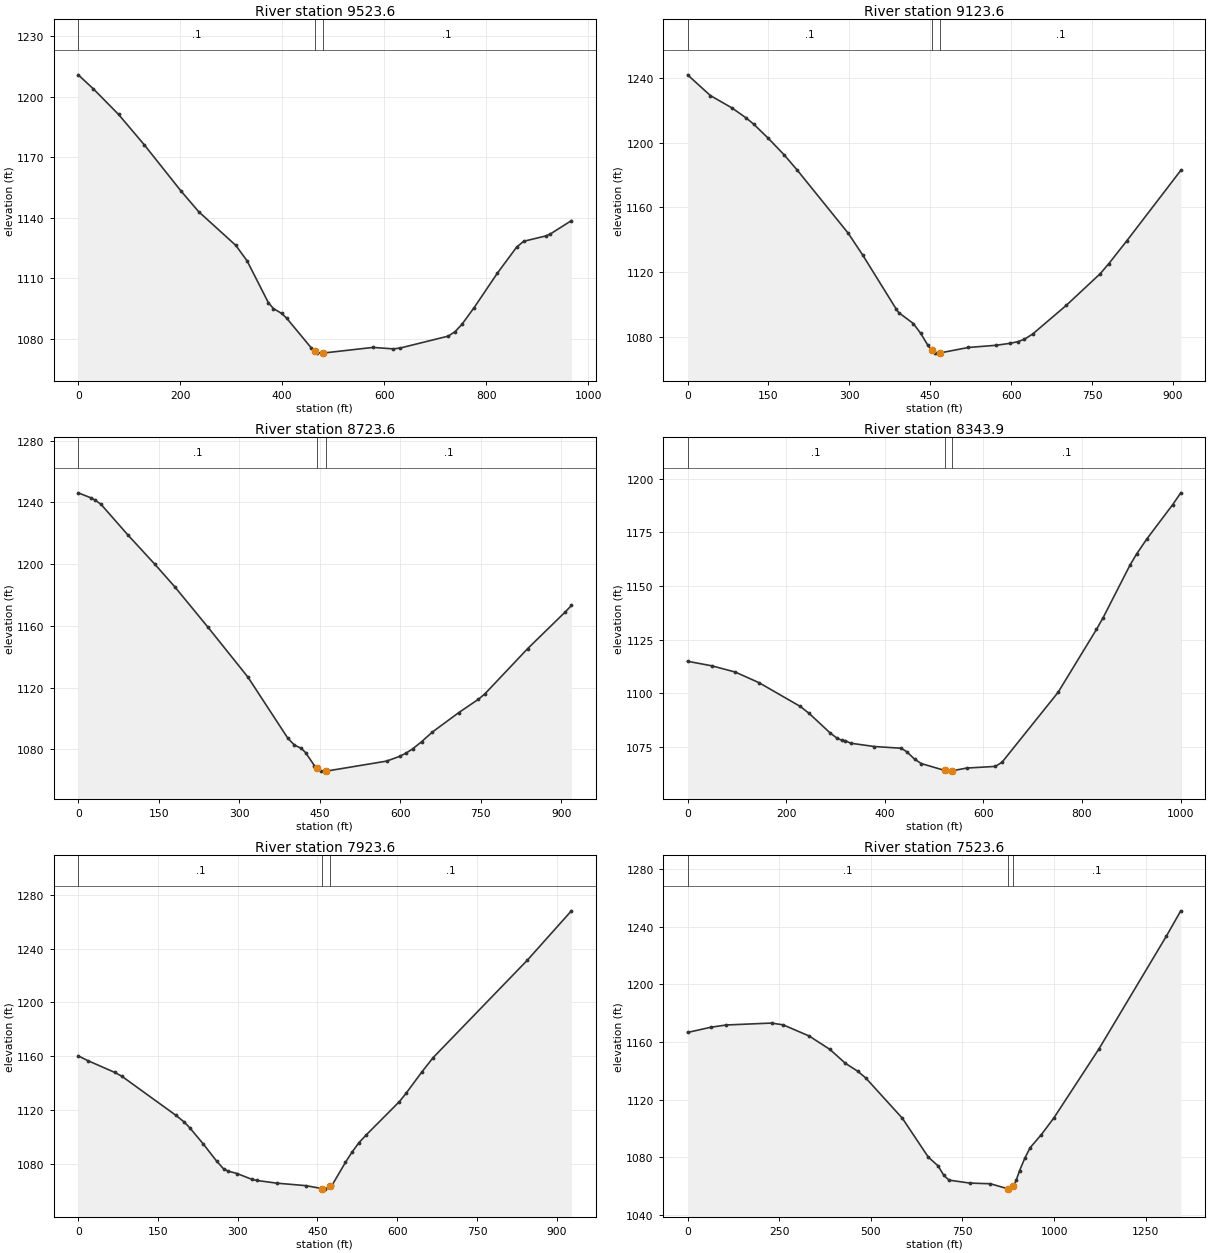
Type RM Length L Ch R = 1 ,9523.6  ,398.817,400,397.379
XS GIS Cut Line= 3
     1676618.868      331453.929     1677019.664      331204.715
     1677458.308      330973.464
#Sta/Elev= 30
       0 1210.74    29.4 1203.89    79.2 1191.14   129.2 1176.25   201.8 1153.22
   236.3 1143.05     309  1126.4   331.1 1118.79   372.8 1098.11   382.8 1095.15
     399 1092.73   408.7 1090.41   456.7  1075.8   464.5 1074.17     469 1073.33
   477.8 1073.08   479.5 1073.09   578.1 1075.91   618.2 1075.18   631.8 1075.62
   725.7 1081.49   739.1  1083.7   752.6 1087.33   776.6 1095.62   822.1 1112.63
   859.9 1125.52   873.7  1128.4   917.2 1131.05     926 1132.02   967.3 1138.63
#Mann= 3 , 0 , 0
       0      .1       0   464.5    .045       0   479.5      .1       0
Bank Sta=464.5,479.5
XS Rating Curve= 0 ,0
Exp/Cntr=0.3,0.1

Type RM Length L Ch R = 1 ,9123.6  ,395.764,400,406.985
XS GIS Cut Line= 3
     1676779.502      331769.397     1677186.086       331553.01
     1677573.421      331316.182
#Sta/Elev= 30
       0 1241.96    42.2 1229.17    82.5 1221.46   109.1 1215.19   122.9 1211.38
   149.8 1202.68   179.5 1192.33   203.6 1182.95   297.7 1144.08   324.6  1130.6
     387 1097.05   391.8 1094.82   418.7 1088.13   432.2 1082.13   445.6  1074.7
   453.1 1071.48   459.1 1069.94   462.6 1069.82   468.1 1069.94   520.8 1073.32
   572.7 1074.69   598.2  1075.9   612.1 1076.87   624.5  1078.4   639.9 1081.61
   702.2 1099.34   765.2 1118.93   781.3 1125.21   814.5 1139.28   914.6 1182.84
#Mann= 3 , 0 , 0
       0      .1       0   453.1    .045       0   468.1      .1       0
Bank Sta=453.1,468.1
XS Rating Curve= 0 ,0
Exp/Cntr=0.3,0.1

Type RM Length L Ch R = 1 ,8723.6  ,384.771,379.645,375.611
XS GIS Cut Line= 3
     1676882.251      332050.113      1677316.11      331919.393
     1677769.229        331812.9
#Sta/Elev= 30
       0 1246.19    23.2 1243.02    30.8 1241.66    42.3 1238.81    92.8  1218.8
   142.4 1200.05   179.6 1185.43   241.6 1159.16     316 1126.85   390.4 1087.24
   402.8 1082.73   415.2 1080.73   423.5 1077.87     440 1069.42   445.6 1067.71
   452.4 1066.07   460.6 1065.91   461.9 1065.88   574.3 1072.36   598.7 1075.46
   610.9 1077.61   623.1 1080.35   639.6 1084.95   659.7  1091.2   708.5 1103.73
   745.1 1112.37   757.3 1115.88   837.1 1145.25   906.3 1168.71   918.6 1173.21
#Mann= 3 , 0 , 0
       0      .1       0   445.6    .045       0   460.6      .1       0
Bank Sta=445.6,460.6
XS Rating Curve= 0 ,0
Exp/Cntr=0.3,0.1

Type RM Length L Ch R = 1 ,8343.9  ,417.717,420.355,423.434
XS GIS Cut Line= 3
     1676922.539      332398.814     1677251.077      332353.324
     1677832.004      332022.473
#Sta/Elev= 30
       0    1115      49  1112.9    96.9 1109.97   144.9 1105.03   228.8 1093.94
   246.5 1090.73   288.7 1081.72   302.7 1079.24   312.7  1078.2   320.2 1078.01
   330.5 1076.85   378.3  1075.3     433  1074.5   444.1 1072.96   460.3 1069.43
     474 1067.36   521.3 1064.16   531.1 1063.83   536.3 1063.98     566 1065.26
   624.3 1066.03   637.9 1068.01   751.5 1100.56   829.2 1129.83   842.9 1135.38
   897.5 1159.91   911.2 1165.16   931.6 1172.05   983.8 1187.97  1000.2 1193.47
#Mann= 3 , 0 , 0
       0      .1       0   521.3    .045       0   536.3      .1       0
Bank Sta=521.3,536.3
XS Rating Curve= 0 ,0
Exp/Cntr=0.3,0.1

Type RM Length L Ch R = 1 ,7923.6  ,403.941,400,394.838
XS GIS Cut Line= 3
     1677203.605      332755.205      1677637.77      332584.097
     1678069.765      332423.477
#Sta/Elev= 30
       0 1160.27      18 1156.73    69.1 1147.87    81.8 1145.15   183.9 1115.94
   199.2 1111.05   209.5 1106.86     235 1094.76   260.5 1081.81   273.3 1076.18
   281.6 1074.47   298.8 1072.63   327.3 1068.19   336.5 1067.44   373.1 1065.48
     428 1063.61   459.2 1061.38   464.6 1061.01   474.2 1063.16   477.4 1063.89
   502.7    1081   515.4 1088.79     528 1095.59   540.7 1100.98     604 1126.15
   616.7 1132.41   646.3 1148.25   667.4 1158.89   844.7 1231.49   927.6 1268.26
#Mann= 3 , 0 , 0
       0      .1       0   459.2    .045       0   474.2      .1       0
Bank Sta=459.2,474.2
XS Rating Curve= 0 ,0
Exp/Cntr=0.3,0.1

Type RM Length L Ch R = 1 ,7523.6  ,444.069,431.58,419.784
XS GIS Cut Line= 3
     1677089.335      333397.065     1677829.443      332918.997
     1678211.575       332655.22
#Sta/Elev= 30
       0 1166.57    63.1 1170.18   105.5 1171.77   229.2  1173.1     261 1171.84
   331.6 1164.12   388.2 1154.82   430.6 1145.15   464.5 1139.62   486.4  1134.9
   586.1 1106.96   656.7 1080.03   683.3 1073.95   699.1 1067.35   713.3 1064.03
   769.8 1061.98   826.3 1061.51   873.6 1058.03   876.9 1057.78   888.6 1060.19
   891.2 1060.94   896.8 1064.15   905.6 1070.55   920.1 1079.32   934.5 1086.56
   965.1 1095.64   999.2  1107.2    1122 1155.06  1306.5 1233.62  1345.4 1251.04
#Mann= 3 , 0 , 0
       0      .1       0   873.6    .045       0   888.6      .1       0
Bank Sta=873.6,888.6
XS Rating Curve= 0 ,0
Exp/Cntr=0.3,0.1

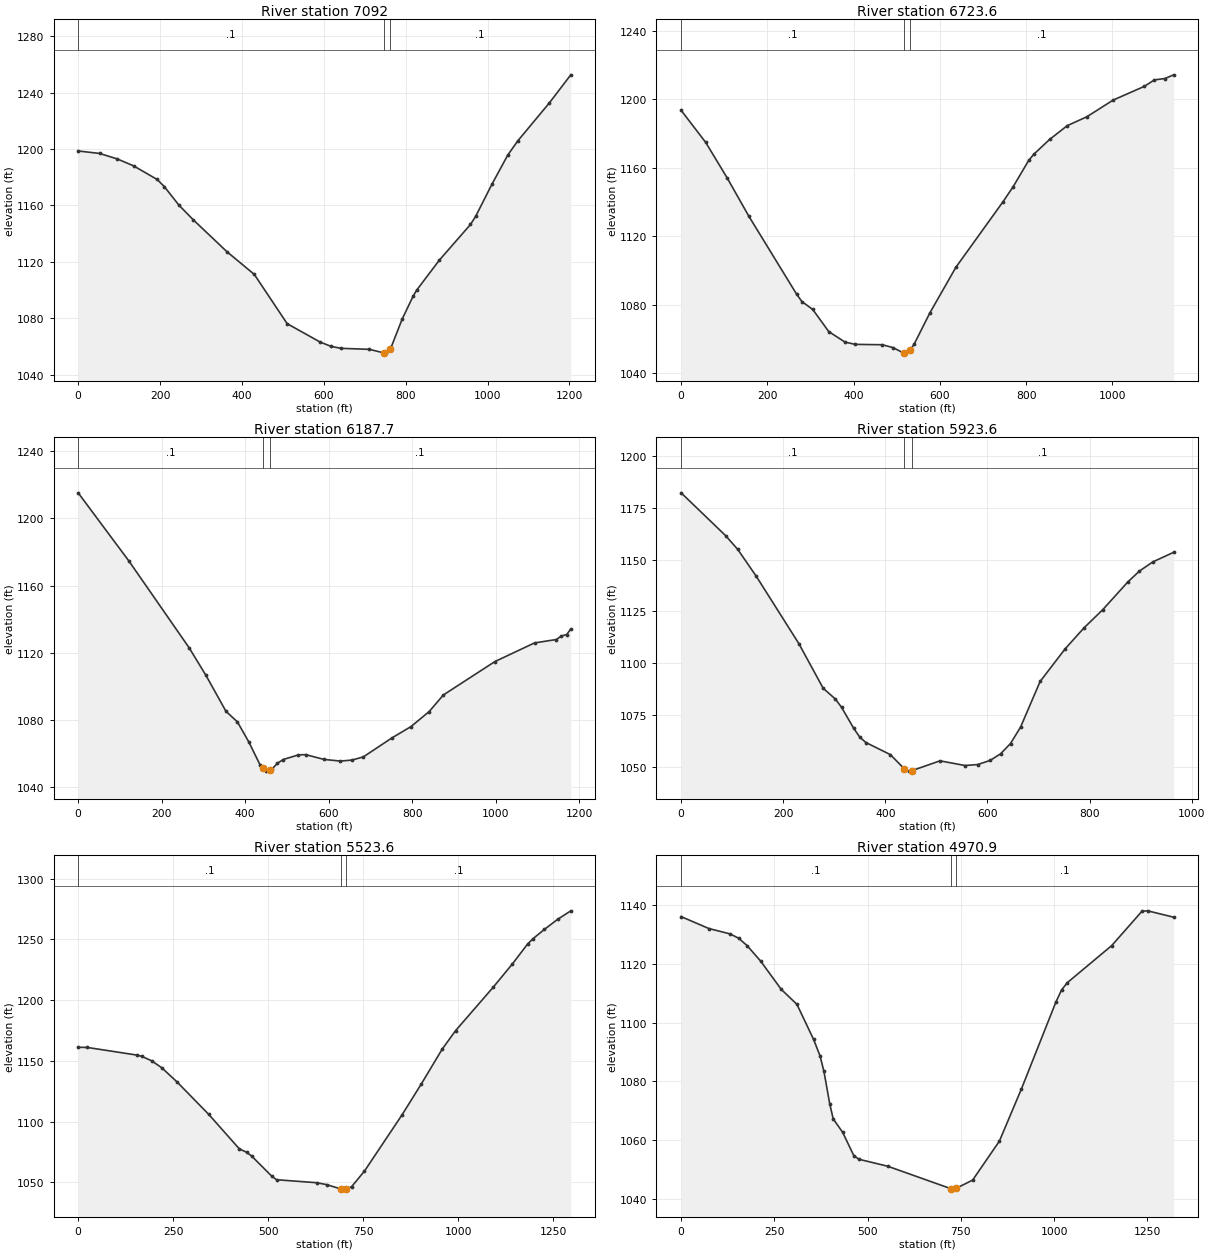
Type RM Length L Ch R = 1 ,7092    ,372.534,368.42,361.629
XS GIS Cut Line= 3
     1677774.211      333811.528      1678155.82      333078.635
      1678287.28      332725.439
#Sta/Elev= 30
       0 1198.61    52.1 1196.88    95.6 1192.97   135.7 1188.01   192.9 1178.42
   210.5 1173.35   245.7 1160.36   280.9 1149.91   363.3 1127.27   430.2 1111.17
   510.5 1076.26   590.8 1063.27   617.6 1060.21   641.8 1058.81   711.3  1058.1
   745.9 1055.62   751.5 1055.41   760.9  1058.2   764.8 1059.84   791.2 1079.43
   817.9 1095.62   826.7    1100     882 1121.23   958.2 1146.54   970.8 1152.29
  1011.1 1175.33  1049.1 1195.62  1073.7 1205.77  1150.5 1232.53  1203.2 1252.55
#Mann= 3 , 0 , 0
       0      .1       0   745.9    .045       0   760.9      .1       0
Bank Sta=745.9,760.9
XS Rating Curve= 0 ,0
Exp/Cntr=0.3,0.1

Type RM Length L Ch R = 1 ,6723.6  ,529.299,535.872,541.358
XS GIS Cut Line= 3
     1678307.453      333781.201     1678460.328        333280.6
     1678570.284      332671.753
#Sta/Elev= 30
       0 1193.68    56.9 1174.96   106.6 1154.24   157.1 1131.75   267.9 1086.17
   280.1 1081.91   305.2 1077.28   342.4 1064.33   379.7 1058.26   403.7 1056.89
   466.6 1056.67   491.4    1055   515.9 1051.82   516.2 1051.77   530.9 1053.41
   540.6 1057.18   576.7 1075.27   637.1 1101.96   745.7 1140.03   769.8 1149.02
     806 1164.44     818 1168.08   854.2 1176.62   895.1 1184.68   940.9 1189.92
  1001.2  1199.6  1073.6 1207.63  1097.4 1211.46  1121.8 1212.26  1142.1 1214.41
#Mann= 3 , 0 , 0
       0      .1       0   515.9    .045       0   530.9      .1       0
Bank Sta=515.9,530.9
XS Rating Curve= 0 ,0
Exp/Cntr=0.3,0.1

Type RM Length L Ch R = 1 ,6187.7  ,273.315,264.128,257.843
XS GIS Cut Line= 3
     1678433.611       333908.14     1678615.774      333659.895
     1679050.455      332904.257
#Sta/Elev= 30
       0 1215.21   121.9 1174.52   265.7 1123.05   305.8 1106.72     354 1085.25
   381.4 1078.95   408.8 1066.96   436.2 1053.09   443.3 1051.28   449.9 1049.68
   458.3 1050.38   463.6 1050.78   477.3 1054.39     491 1056.59   527.6 1059.34
     545  1059.5   588.4 1056.66     628 1055.65   655.4 1056.26   682.8 1058.13
   751.2  1069.4   797.1 1076.19   840.6 1085.12   874.5 1094.97   997.8 1114.83
  1092.8 1125.93  1144.9 1127.95  1157.2 1130.06  1169.9  1130.9  1179.7 1134.23
#Mann= 3 , 0 , 0
       0      .1       0   443.3    .045       0   458.3      .1       0
Bank Sta=443.3,458.3
XS Rating Curve= 0 ,0
Exp/Cntr=0.3,0.1

Type RM Length L Ch R = 1 ,5923.6  ,392.232,400,404.488
XS GIS Cut Line= 3
     1678887.408      334026.804     1678941.461      333585.694
      1679070.52      333081.409
#Sta/Elev= 30
       0 1182.38      87 1161.72   110.9 1155.03   146.8 1142.17   230.5  1109.5
   278.3 1087.84   302.3 1082.61   314.2 1078.66   338.2 1068.43   350.1 1064.17
   362.1 1061.59   409.9 1055.75   436.9 1048.97   445.8 1047.77   451.9 1047.99
   507.1 1052.75   556.1 1050.49   580.7 1050.94   605.2 1052.94   625.7 1056.13
   645.2 1061.13   664.8 1069.01   703.2 1091.15   752.2 1106.91     789 1117.02
   825.8 1125.84   874.8 1139.22   897.6 1144.52   923.8 1148.95   964.9 1153.63
#Mann= 3 , 0 , 0
       0      .1       0   436.9    .045       0   451.9      .1       0
Bank Sta=436.9,451.9
XS Rating Curve= 0 ,0
Exp/Cntr=0.3,0.1

Type RM Length L Ch R = 1 ,5523.6  ,549.642,552.678,558.318
XS GIS Cut Line= 3
     1678972.111       334281.59     1679272.498      333651.053
      1679535.68      333114.016
#Sta/Elev= 30
       0  1161.2    24.4 1161.05   154.3 1154.79   167.4 1153.77   193.7 1150.01
     220 1144.33   259.5  1132.9   343.9  1105.9   424.1 1077.63   443.6 1074.76
   456.7 1071.67   509.3  1055.2   522.1 1052.22   627.7 1049.77     654  1048.2
   690.9 1044.67   705.9 1044.49   719.9  1046.6   753.5 1059.34   852.1 1105.47
     903 1130.97   957.9 1159.61   993.1 1174.83  1091.9 1210.46    1143 1229.85
  1182.6 1246.05  1197.1 1250.54  1226.7 1258.12    1262 1266.49  1296.5 1273.47
#Mann= 3 , 0 , 0
       0      .1       0   690.9    .045       0   705.9      .1       0
Bank Sta=690.9,705.9
XS Rating Curve= 0 ,0
Exp/Cntr=0.3,0.1

Type RM Length L Ch R = 1 ,4970.9  ,244.502,247.322,247.782
XS GIS Cut Line= 3
     1679353.721      334562.111     1679729.537      333943.153
     1680109.359       333482.99
#Sta/Elev= 30
       0 1136.16    74.4  1132.1   131.3 1130.27   154.2  1128.8   177.1 1126.26
   213.3 1120.99   268.6 1111.35   310.5 1106.28   355.2 1094.32   372.5  1088.7
     383 1083.39   398.4 1072.43   407.8 1067.24     433 1062.69   463.3 1054.66
   477.2 1053.47     554 1051.11   722.3 1043.51   726.7 1043.31   737.3 1043.55
   781.7 1046.41   853.3 1059.65   912.6  1077.5  1004.7    1107  1020.1 1111.19
  1035.5 1113.65  1154.7 1126.31  1235.6 1137.99    1251 1138.13  1320.8 1135.95
#Mann= 3 , 0 , 0
       0      .1       0   722.3    .045       0   737.3      .1       0
Bank Sta=722.3,737.3
XS Rating Curve= 0 ,0
Exp/Cntr=0.3,0.1

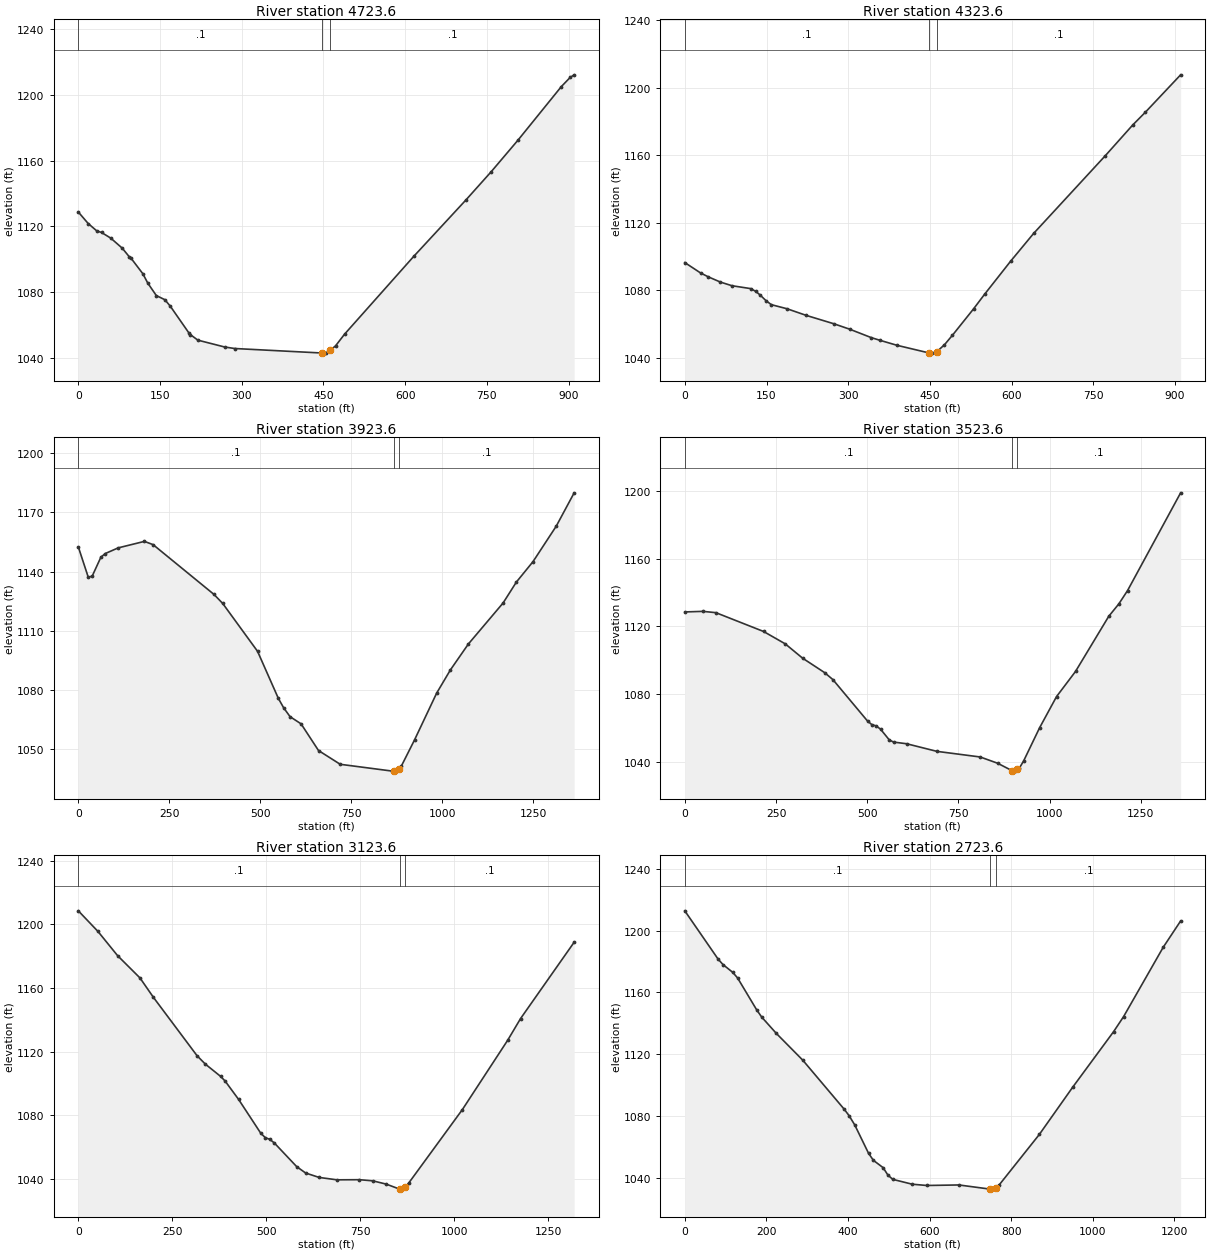
Type RM Length L Ch R = 1 ,4723.6  ,402.367,400,397.828
XS GIS Cut Line= 3
     1679648.566      334405.363     1679944.935      334059.947
     1680248.724       333721.25
#Sta/Elev= 30
       0 1128.74    18.1 1121.75    33.7 1117.32    42.6  1116.3    59.5 1112.89
    80.7 1106.74    93.1  1101.7    96.3 1100.86   118.4 1091.23   127.6 1085.46
   143.2 1077.94   158.9 1075.42   168.9 1071.44   202.6 1055.39   205.8 1054.17
   219.4 1050.84   268.4 1046.69   286.8 1045.76   447.6 1043.01   454.1 1042.95
   462.6 1044.81   472.1 1047.35   488.8 1054.52   615.6 1101.76   711.3 1136.03
   757.9 1153.28     807 1172.45   886.7 1205.07   902.7 1210.56   910.1 1212.17
#Mann= 3 , 0 , 0
       0      .1       0   447.6    .045       0   462.6      .1       0
Bank Sta=447.6,462.6
XS Rating Curve= 0 ,0
Exp/Cntr=0.3,0.1

Type RM Length L Ch R = 1 ,4323.6  ,411.019,400,390.598
XS GIS Cut Line= 3
     1680002.025      334676.636     1680260.731      334302.026
     1680530.622      333935.772
#Sta/Elev= 30
       0 1096.34    28.9 1090.21    43.3 1087.86    65.5 1084.78    86.6 1082.63
   120.7 1080.94   129.9 1079.36   137.8 1077.28   149.1 1073.78   158.8 1071.42
   187.6    1069   223.1 1065.05   273.7  1060.1   303.1 1056.84   342.6 1051.87
     358 1050.34   389.6 1047.35   447.8 1042.87   453.5 1042.72   462.8 1043.62
   476.7 1047.69   491.4 1053.33     530 1068.89   550.4  1077.6   597.9 1097.06
   640.3 1113.58   771.6  1159.5   822.4 1177.85   845.4 1185.34   910.2 1207.51
#Mann= 3 , 0 , 0
       0      .1       0   447.8    .045       0   462.8      .1       0
Bank Sta=447.8,462.8
XS Rating Curve= 0 ,0
Exp/Cntr=0.3,0.1

Type RM Length L Ch R = 1 ,3923.6  ,403.16,400,394.543
XS GIS Cut Line= 3
     1680488.441      335391.038     1680590.031      334523.598
     1680695.807      334046.911
#Sta/Elev= 30
       0 1152.48    27.2 1137.19      38 1137.68    61.9 1147.27    73.8 1149.13
   109.7 1152.03   181.4  1155.3   205.3 1153.66   372.7 1128.41   396.6 1123.84
   492.2  1099.6   549.4 1075.72   563.9 1070.97   581.5 1066.48   611.7 1062.85
   659.6 1049.33   719.3 1042.35   862.8 1038.89   865.9 1038.92   880.9 1040.17
   886.9 1041.37   923.4 1054.74   984.2 1078.46  1021.9  1090.2  1071.2 1103.31
  1166.6 1124.11  1203.1 1134.71  1248.8 1145.07  1312.6 1163.05  1361.7 1179.91
#Mann= 3 , 0 , 0
       0      .1       0   865.9    .045       0   880.9      .1       0
Bank Sta=865.9,880.9
XS Rating Curve= 0 ,0
Exp/Cntr=0.3,0.1

Type RM Length L Ch R = 1 ,3523.6  ,397.574,400,402.483
XS GIS Cut Line= 3
     1681009.048      335391.038      1680987.25      334487.292
     1680976.482      334032.421
#Sta/Elev= 30
       0 1128.48    49.6 1128.82    85.2 1128.05   215.9 1116.93   275.2 1109.63
   322.7 1101.18   383.3  1092.6   405.9 1088.49   500.9 1063.98   512.8 1061.86
   524.6 1061.11   536.5 1059.19   560.3 1052.88   572.1 1051.56   607.8 1050.58
   690.9 1046.08   809.7 1042.75   857.2 1039.07   896.5 1034.72     904 1034.39
   911.5 1035.36   916.6 1036.07   928.4 1040.28   972.5 1060.03  1018.9 1078.45
  1070.9  1093.3    1162  1125.9  1189.7 1133.25  1213.5 1141.09    1359 1198.88
#Mann= 3 , 0 , 0
       0      .1       0   896.5    .045       0   911.5      .1       0
Bank Sta=896.5,911.5
XS Rating Curve= 0 ,0
Exp/Cntr=0.3,0.1

Type RM Length L Ch R = 1 ,3123.6  ,403.123,400,393.186
XS GIS Cut Line= 3
     1681310.007      335350.576     1681381.735      334491.389
     1681421.114      334036.011
#Sta/Elev= 30
       0 1208.49    52.1 1195.57   104.5 1180.29     164 1166.29   199.8 1154.07
     316 1117.33     338 1112.08   378.5 1104.38   390.4 1101.49   426.4  1089.9
   485.7 1068.52   497.6 1065.84   509.5 1064.75   521.5  1062.5     581 1047.61
   604.8  1043.6   640.6 1040.82   688.2 1039.31   747.8 1039.39   783.6 1038.67
   819.3 1036.61   854.7 1033.48     855 1033.46     867 1033.97   869.7 1034.74
   878.9 1037.22  1021.9  1083.5  1142.3 1127.05  1176.8 1140.77  1319.3 1188.75
#Mann= 3 , 0 , 0
       0      .1       0   854.7    .045       0   869.7      .1       0
Bank Sta=854.7,869.7
XS Rating Curve= 0 ,0
Exp/Cntr=0.3,0.1

Type RM Length L Ch R = 1 ,2723.6  ,333.618,337.264,339.84
XS GIS Cut Line= 3
     1681817.952      335256.849     1681775.441      334502.802
     1681677.595      334053.199
#Sta/Elev= 30
       0 1212.88    81.7 1181.59    93.6 1178.08   117.4 1173.06   129.3 1169.45
   176.6 1148.57   188.8 1143.98   224.4 1133.49   289.2 1116.16   390.9 1084.35
   402.8 1080.18   416.6 1074.22   450.4 1055.87   462.3 1051.29   486.1 1046.56
   497.9 1041.74   509.8 1038.97   557.4 1035.84   593.1 1035.01   671.9 1035.35
   747.7 1032.68   750.7 1032.65   762.7 1033.52   771.2 1035.56     869 1068.04
   950.8 1098.65  1051.3 1134.71  1075.6 1144.37  1172.8 1189.32  1215.4  1206.3
#Mann= 3 , 0 , 0
       0      .1       0   747.7    .045       0   762.7      .1       0
Bank Sta=747.7,762.7
XS Rating Curve= 0 ,0
Exp/Cntr=0.3,0.1

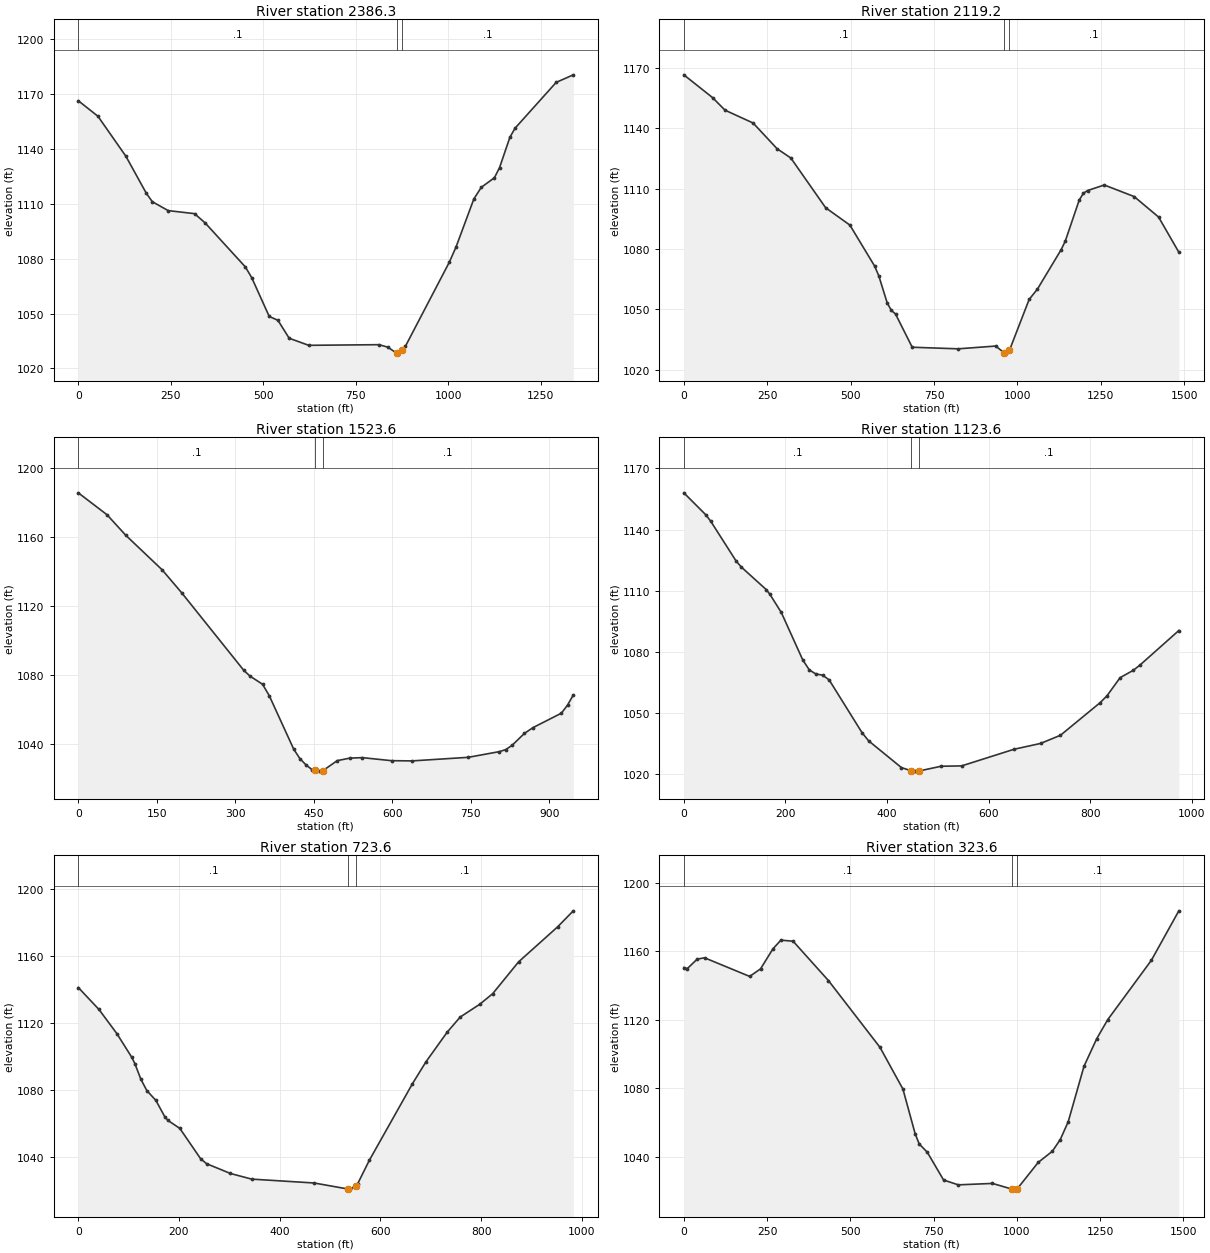
Type RM Length L Ch R = 1 ,2386.3  ,274.65,267.142,259.634
XS GIS Cut Line= 3
     1682065.424      335252.041     1682062.897      334231.046
     1681898.067      333960.309
#Sta/Elev= 30
       0 1166.43    53.1 1157.94   128.7 1136.05   183.7 1115.88   200.1  1111.2
     243 1106.33   314.3 1104.67   342.9  1099.6   451.6 1075.53   468.6 1069.74
   516.1 1048.46   539.8 1046.31     570 1036.53   622.9 1032.66   812.9 1033.01
   836.7 1031.65   860.4 1028.39   861.1 1028.44   876.1 1030.02   884.1 1032.09
  1002.9 1078.11    1021 1086.39  1069.3 1112.74  1089.4 1119.07  1124.9 1124.32
  1138.8  1129.9  1166.6  1146.4  1180.5 1151.37  1291.7 1176.45    1338 1180.59
#Mann= 3 , 0 , 0
       0      .1       0   861.1    .045       0   876.1      .1       0
Bank Sta=861.1,876.1
XS Rating Curve= 0 ,0
Exp/Cntr=0.3,0.1

Type RM Length L Ch R = 1 ,2119.2  ,588.991,595.594,605.214
XS GIS Cut Line= 3
     1682623.756      335217.248      1682429.16      334653.679
     1682147.511      333811.625
#Sta/Elev= 30
       0 1166.64    86.1 1155.31   123.5 1149.06   207.7 1142.68   279.6 1129.89
   320.8 1125.28   425.1 1100.56   497.8 1091.92     572 1071.54   584.5 1066.71
   609.6 1053.27   622.1  1049.5   634.7 1047.72   684.7 1031.18   822.4 1030.39
   935.1 1031.77   961.2 1028.29   965.5 1028.25   976.2 1029.62  1035.3 1054.95
  1060.3 1060.12  1131.3 1079.71  1143.8 1084.01  1185.5 1104.39    1198 1107.75
  1210.5  1109.1  1260.6 1111.86  1350.2  1106.1  1423.4 1095.92  1484.1 1078.43
#Mann= 3 , 0 , 0
       0      .1       0   961.2    .045       0   976.2      .1       0
Bank Sta=961.2,976.2
XS Rating Curve= 0 ,0
Exp/Cntr=0.3,0.1

Type RM Length L Ch R = 1 ,1523.6  ,404.212,400,389.608
XS GIS Cut Line= 3
     1682834.819      334980.737     1682814.029       334521.31
      1682855.01      334037.299
#Sta/Elev= 30
       0 1185.78    54.9 1173.04    90.5 1161.18   160.1 1141.07   197.5 1127.71
   316.3 1082.58   328.2 1079.26     352 1074.55   364.8  1067.9   411.4 1036.91
   423.3 1031.35   435.2 1027.65   447.1  1024.8   452.4 1024.47     459 1024.09
   467.4 1024.41   494.7 1030.19   518.5 1031.64   542.4 1031.93   598.3 1030.16
   637.4 1030.03   744.9 1032.11   804.5 1035.43   816.4  1036.6   828.3    1039
   852.2 1046.02   868.6 1049.38   922.7 1057.74   934.6 1062.48   945.5 1068.35
#Mann= 3 , 0 , 0
       0      .1       0   452.4    .045       0   467.4      .1       0
Bank Sta=452.4,467.4
XS Rating Curve= 0 ,0
Exp/Cntr=0.3,0.1

Type RM Length L Ch R = 1 ,1123.6  ,392.342,400,417.039
XS GIS Cut Line= 3
     1683357.291      334914.995      1683175.31      334498.281
      1682958.99      334025.339
#Sta/Elev= 30
       0 1158.04    43.6 1147.17    52.9 1144.12   102.9 1124.61   113.2 1121.63
   162.2 1110.58   169.5 1108.26   191.9 1099.36   234.2 1076.07   247.2 1071.14
   260.1 1069.17   273.1 1068.61   286.1  1066.3   350.8 1040.43   363.8  1036.4
   428.6 1023.24   447.2 1021.76   455.8 1021.52   462.2 1021.54   506.7 1023.92
   547.1 1024.08   650.3 1032.25   702.5  1035.1   741.7 1039.11     820 1055.14
   833.1 1058.41   859.2 1067.38   885.3 1071.01   898.4 1073.58   974.8 1090.49
#Mann= 3 , 0 , 0
       0      .1       0   447.2    .045       0   462.2      .1       0
Bank Sta=447.2,462.2
XS Rating Curve= 0 ,0
Exp/Cntr=0.3,0.1

Type RM Length L Ch R = 1 ,723.6   ,394.833,400,373.761
XS GIS Cut Line= 3
     1683440.666      334895.766     1683440.098      334352.061
     1683611.141      333947.377
#Sta/Elev= 30
       0 1141.42    41.1  1128.3    76.7 1113.86   106.2 1099.77   112.3 1096.05
   124.2 1086.72   136.1  1079.9   154.1 1074.03   171.7 1064.34   177.9 1062.11
   201.7 1057.31   242.9 1039.24   254.8 1036.24   302.3  1030.4   344.3 1027.05
   468.5 1024.73   536.2 1021.11   539.7 1021.07   551.2 1022.93   554.8 1024.23
   578.1 1038.32   663.5 1083.92   690.7 1097.15   732.7 1114.78   758.5 1123.78
   797.2 1131.39     823 1137.73   874.5 1156.74   951.9 1177.59   983.1 1187.19
#Mann= 3 , 0 , 0
       0      .1       0   536.2    .045       0   551.2      .1       0
Bank Sta=536.2,551.2
XS Rating Curve= 0 ,0
Exp/Cntr=0.3,0.1

Type RM Length L Ch R = 1 ,323.6   ,315.138,298.18,285.926
XS GIS Cut Line= 3
     1683503.411      335446.637     1683735.723      334480.485
     1683756.568      333988.576
#Sta/Elev= 30
       0 1150.43    10.5 1149.83    40.2 1155.36    62.2 1156.12   197.7 1145.24
   230.3 1149.67   267.4 1161.34   291.3 1166.43     328 1165.82     434 1142.85
     589 1103.78   657.7 1079.45   694.3 1053.44   706.5 1047.42   730.9 1042.55
   779.8 1026.32   823.9  1023.5   926.6 1024.33   985.2    1021   986.2    1021
  1001.2 1021.25  1063.7 1036.58  1106.4 1043.14  1130.1 1049.98  1153.9 1060.34
  1201.4 1092.82  1239.7 1108.94  1272.7 1120.03  1403.5 1154.65    1486 1183.56
#Mann= 3 , 0 , 0
       0      .1       0   986.2    .045       0  1001.2      .1       0
Bank Sta=986.2,1001.2
XS Rating Curve= 0 ,0
Exp/Cntr=0.3,0.1

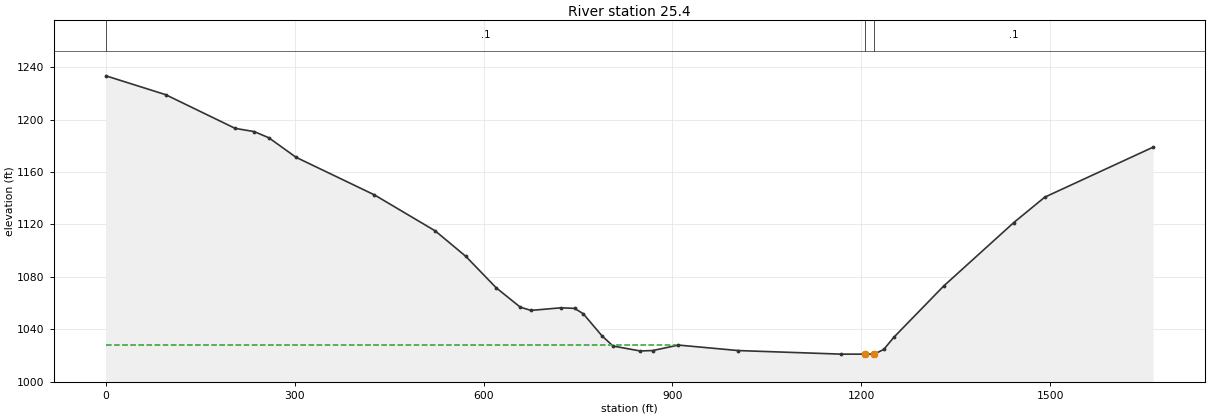
Type RM Length L Ch R = 1 ,25.4    ,16.739,25.382,34.024
XS GIS Cut Line= 3
     1684600.223      335446.637     1684160.487       334708.69
     1683768.768      334006.124
#Sta/Elev= 30
       0 1233.34    94.8 1218.98   205.4 1193.24   235.6  1190.8   258.8 1186.08
   302.1 1171.17   426.5 1142.52   523.2 1115.01   571.7 1095.62     620 1071.61
   658.3 1056.82   675.3 1054.36   722.6 1056.34   744.4 1055.93   758.2 1051.85
   788.2 1034.88   805.5 1027.19   848.8 1023.41   868.6 1023.74   909.4 1027.91
  1004.5 1023.72  1167.7    1021  1205.5    1021  1220.5    1021  1235.6 1024.58
    1252 1034.04  1330.8 1072.95  1442.2  1121.4  1491.4 1140.78  1663.4 1178.89
#Mann= 3 , 0 , 0
       0      .1       0  1205.5    .045       0  1220.5      .1       0
#XS Ineff= 2 , 0
           907.8 1028.23
Permanent Ineff=
       F       F
Bank Sta=1205.5,1220.5
XS Rating Curve= 0 ,0
Exp/Cntr=0.3,0.1

Chan Stop Cuts=-1
Use User Specified Reach Order=0